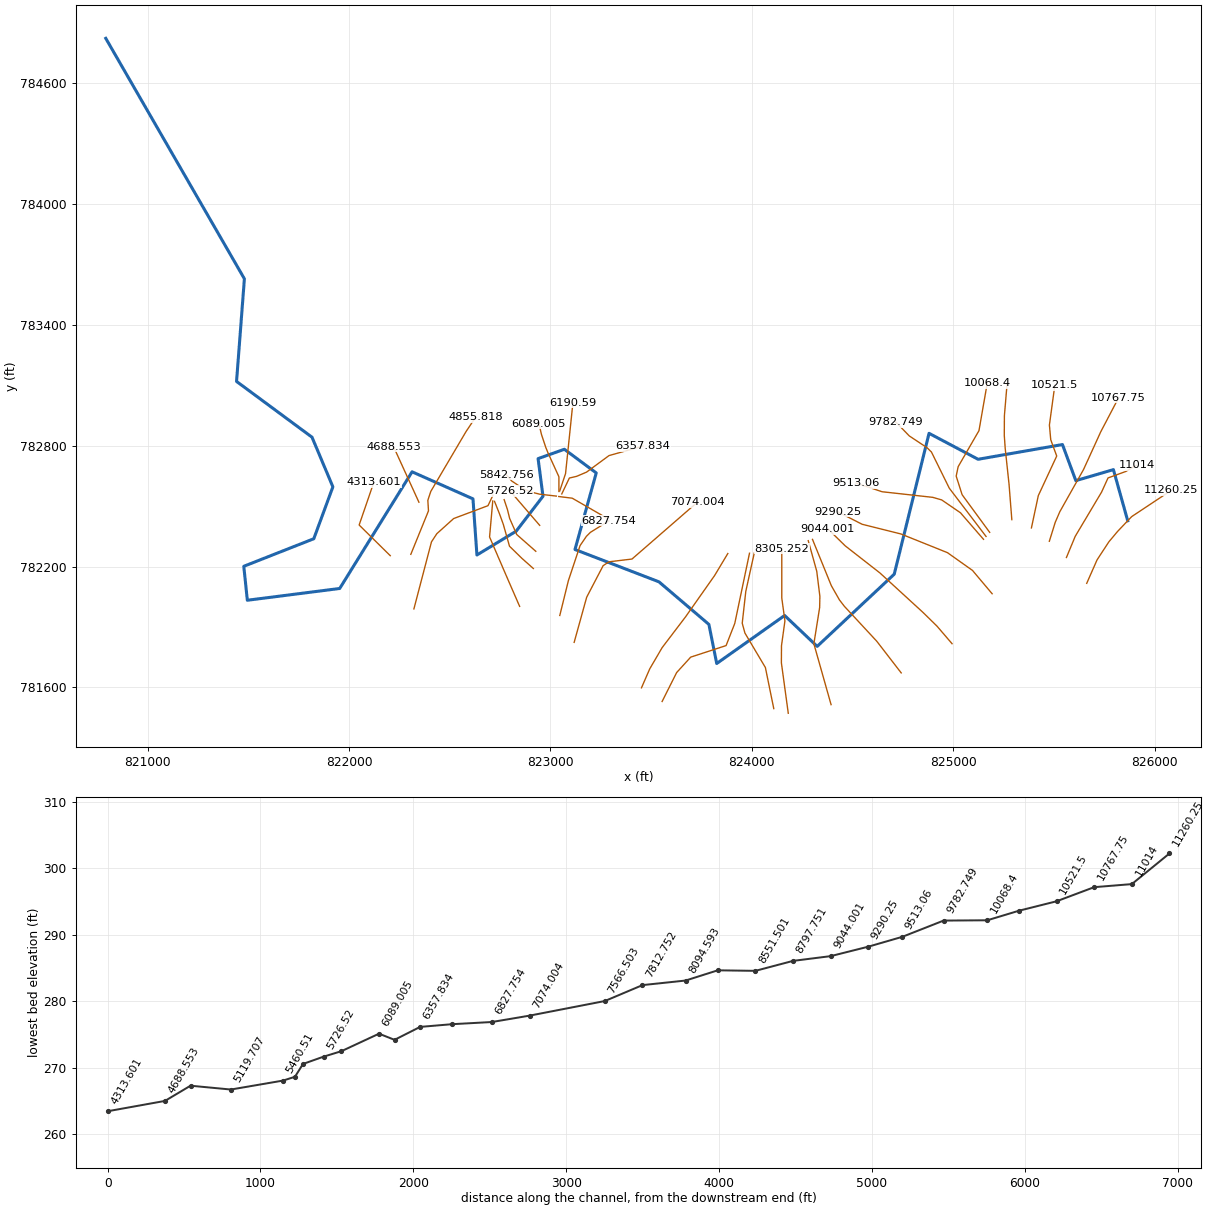
--- 17380_ras.prj (project) ---

Proj Title=17380
Current Plan=p01
Default Exp/Contr=0.3,0.1
English Units
Geom File=g01
Flow File=f01
Plan File=p01
Y Axis Title=Elevation
X Axis Title(PF)=Main Channel Distance
X Axis Title(XS)=Station
BEGIN DESCRIPTION:
RFD model 17380 exported to HEC-RAS
END DESCRIPTION:

--- 17380_ras.p01 (plan) ---

Plan Title=Plan 01
Program Version=4.10
Short Identifier=Plan 01
Geom File=g01
Flow File=f01
Subcritical Flow
Calc Critical at every XS
Secant Critical Depth

--- 17380_ras.f01 (steady flow) ---

Flow Title=Flow 01
Program Version=5.01
Number of Profiles= 6
Profile Names=10yr,25yr,50yr,100yr,100plus,500yr
River Rch & RM=17380,31,11260.25
 1373.81 2196.25 2968.65 3663.88 5349.27 6868.81
River Rch & RM=17380,31,   11014
 1382.25 2209.92  2987.3 3687.06  5383.1 6906.71
River Rch & RM=17380,31, 10521.5
 1439.32 2302.76 3114.31 3845.27  5614.1 7166.24
River Rch & RM=17380,31,10275.25
  1442.2 2307.41 3120.66 3853.17 5625.62 7179.06
River Rch & RM=17380,31, 10068.4
 1450.38 2320.74 3138.91 3875.92 5658.84 7216.31
River Rch & RM=17380,31,9782.749
 1455.75 2329.48 3150.87 3890.84 5680.62 7240.71
River Rch & RM=17380,31, 9513.06
 1461.36 2338.63 3163.39 3906.45 5703.41 7266.24
River Rch & RM=17380,31, 9290.25
 1464.74  2344.1 3170.87 3915.73 5716.97 7281.31
River Rch & RM=17380,31,9044.001
 1478.51 2366.41 3201.31 3953.57 5772.22 7342.62
River Rch & RM=17380,31,8797.751
 1485.12 2377.18 3216.06 3971.96 5799.06 7372.62
River Rch & RM=17380,31,8551.501
 1529.51 2448.22 3312.25 4090.67 5972.37 7560.78
River Rch & RM=17380,31,8305.252
 1533.02 2453.95 3320.11 4100.48  5986.7 7576.76
River Rch & RM=17380,31,8094.593
 1535.28 2457.64 3325.16 4106.78  5995.9 7587.02
River Rch & RM=17380,31,7812.752
 1548.14 2478.48 3353.61 4142.14 6047.53 7643.94
River Rch & RM=17380,31,7566.503
  1550.9 2482.98 3359.77 4149.83 6058.76 7656.44
River Rch & RM=17380,31,7074.004
 1562.65 2502.15 3386.07 4182.66 6106.68 7709.76
River Rch & RM=17380,31,6827.754
 1565.89 2507.44 3393.33 4191.72 6119.91 7724.49
River Rch & RM=17380,31,6564.114
 1570.28 2514.66 3403.27 4204.16 6138.08 7744.85
River Rch & RM=17380,31,6357.834
 1571.77 2517.09  3406.6 4208.33 6144.17 7751.64
River Rch & RM=17380,31, 6190.59
 1711.79 2747.02  3723.1 4604.73 6722.91 8395.88
River Rch & RM=17380,31,6089.005
 1712.74 2748.59 3725.26 4607.44 6726.86 8400.26
River Rch & RM=17380,31,5842.756
 1716.08 2754.07 3732.81 4616.91 6740.69 8415.59
River Rch & RM=17380,31, 5726.52
 1717.03 2755.64 3734.98 4619.62 6744.65 8419.97
River Rch & RM=17380,31, 5539.06
 1719.18 2759.17 3739.84 4625.72 6753.54 8429.82
River Rch & RM=17380,31,5119.707
 2659.37 4239.72 5723.83 7049.0110291.5511980.84
River Rch & RM=17380,31,4855.818
 2665.16 4249.32 5737.11 7065.7310315.9612006.55
River Rch & RM=17380,31,4688.553
 2667.97 4253.97 5743.54 7073.8110327.7612018.93
River Rch & RM=17380,31,4313.601
 2670.36 4257.91 5748.99 7080.6510337.7412029.39
Boundary for River Rch & Prof#=17380,31,1
Up Type= 0
Dn Type= 2
Boundary for River Rch & Prof#=17380,31,2
Up Type= 0
Dn Type= 2
Boundary for River Rch & Prof#=17380,31,2
Up Type= 0
Dn Type= 2
Boundary for River Rch & Prof#=17380,31,2
Up Type= 0
Dn Type= 2
Boundary for River Rch & Prof#=17380,31,2
Up Type= 0
Dn Type= 2
Boundary for River Rch & Prof#=17380,31,2
Up Type= 0
Dn Type= 2

--- 17380_ras.g01 (geometry) ---

Geom Title=17380
Program Version=4.10

River Reach=17380,31
Reach XY= 30
825865.606518387782427.314629385825794.565173092782681.215438417
825607.911357641782626.616741921825541.564460964782805.721349106
825122.787032667782732.617723819824879.351630092782861.427410366
824706.540458562782162.103348821824324.017549396781803.817024048
824162.557207854 781957.19008587823825.357777388781718.844372071
823786.546776475781913.054184921823538.608687728782124.341454348
823121.827516468782284.641280998823227.393013597782664.762769945
823069.138545931782782.293775266822938.720368981782735.899957369
822963.026916507782549.001493042822829.927976072 782375.69420208
822635.098605337 782257.52814633822615.436690481782536.175297342
  822313.1702168782670.448862365821953.922344449782091.296363123
821495.420408757782032.797837172821477.857328595782201.403406975
821825.361657294782338.166473712821920.100025775  782595.7680464
821816.404947819782842.308010582821441.849458545 783119.00547495
821480.844311447783628.445154774820792.705499562784822.152758404

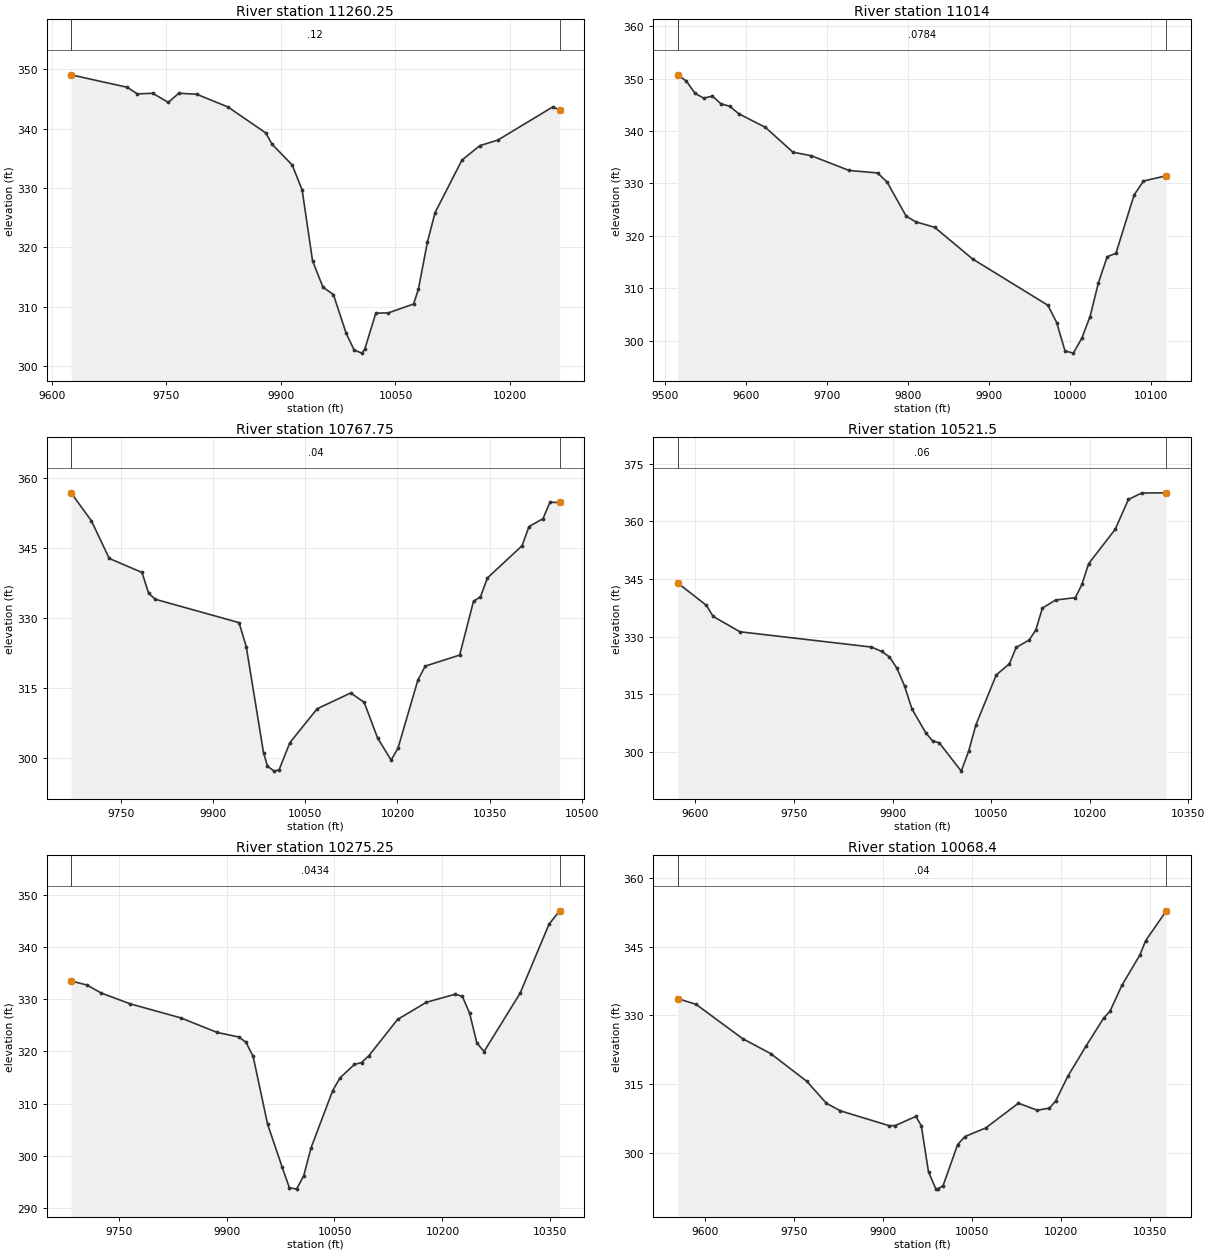
Type RM Length L Ch R = 1 ,11260.25,246.249600,246.249600,246.249600
XS GIS Cut Line= 6
825662.032879073782116.834909905825713.308932933782233.137497922
825772.041668738782322.966824106825815.573772543782374.850934849
825885.312966477782448.083915691826082.057762644782578.653657393
#Sta/Elev= 30
9625.116349.05499698.495346.96459711.891345.84539732.054345.95199752.388344.4176
9766.275345.96259789.687345.78489830.549343.6447 9879.95339.28649888.551 337.345
9914.658333.8877 9927.72 329.6829941.376317.74419955.003313.31149968.644312.0782
9985.483305.52519995.927302.717210005.98302.211310009.79302.884210024.22308.9485
10040.76308.9833 10073.7310.483810079.92312.939210091.89320.944110101.78325.8476
10137.02334.699210160.52337.137710184.02338.071210256.24343.675210264.96343.1242
#Mann= 3 , 0 , 0
9625.116    0.12       09625.116    0.12       010264.96    0.12       0
#XS Ineff= 2 , 0
       0                               0
Bank Sta=9625.116,10264.96
Exp/Cntr=0.3,0.1

Type RM Length L Ch R = 1 ,   11014,246.249600,246.249600,246.249600
XS GIS Cut Line= 6
825561.294646837782245.047205504825605.047757718782350.292913371
825735.878232189782569.878045319825767.857873807782640.075817326
825855.615901474 782671.92444116825908.781205713782702.792086227
#Sta/Elev= 30
9515.349350.7453 9525.98349.53099536.661347.20579547.342346.28789558.023346.6837
9568.704345.20479579.503344.73249590.521343.32529623.574340.70459657.507335.9716
9680.254335.29119726.775332.48419761.986332.01249773.724330.27119797.198323.7874
9808.935322.68669832.409321.63519879.357315.57759972.279306.74219983.106303.4543
 9993.37298.032110003.63297.606210013.96300.403510024.28304.582610034.69311.0718
10045.49 316.00810056.29316.6735 10078.7327.810310090.25330.4689 10118.5331.4778
#Mann= 3 , 0 , 0
9515.349  0.0784       09515.349  0.0784       0 10118.5  0.0784       0
#XS Ineff= 2 , 0
       0                               0
Bank Sta=9515.349,10118.5
Exp/Cntr=0.3,0.1

Type RM Length L Ch R = 1 ,10767.75,246.249600,246.249600,246.249600
XS GIS Cut Line= 6
825476.477209714782325.674474556825505.832374474782419.853622934
 825528.59316503782472.543584089825646.367194353782682.008504254
825731.422349854782868.432678721825820.734858207  783038.8668169
#Sta/Elev= 30
9669.502356.91289702.595350.88369731.469 342.8289784.723339.81429795.616335.3288
9806.509334.05219942.457329.03929954.247323.86849982.262301.1185  9988.7 298.216
9999.649297.146710007.61297.435110025.06303.2458 10069.5310.5447 10124.1313.9335
10145.94311.909710167.78304.248210189.68 299.52910200.78302.0462 10233.3 316.749
10245.17 319.69910301.11 322.07310323.65333.648410334.92334.553910346.18338.6315
10402.52345.548210413.83349.673410436.52351.350810447.87354.8758 10463.6354.8508
#Mann= 3 , 0 , 0
9669.502    0.04       09669.502    0.04       0 10463.6    0.04       0
#XS Ineff= 2 , 0
       0                10085.66       0
Bank Sta=9669.502,10463.6
Exp/Cntr=0.3,0.1

Type RM Length L Ch R = 1 , 10521.5,246.249600,246.249600,246.249600
XS GIS Cut Line= 6
825387.531156206782391.910897357825421.641463284782551.966790399
825513.076153867782748.688843162825483.490000111782829.356978118
825476.846328017782902.551608687825503.878908375783101.560240137
#Sta/Elev= 30
9573.095 343.9499616.598338.15959626.817335.28449667.696331.2754 9867.81327.3026
9883.756326.14529895.224324.72749906.691321.77339918.159317.19159929.456311.2156
 9950.63304.96789960.853302.90419970.968 302.391 10004.5295.024810015.81  300.24
10026.86307.082610057.85320.060810077.95 322.97210087.97327.1843   10108329.1439
10118.01331.753510128.04337.439410148.08339.528310178.14340.152710188.21343.5907
10198.32348.965610238.76357.905910258.98365.699510279.31367.3737 10316.7367.4181
#Mann= 3 , 0 , 0
9573.095    0.06       09573.095    0.06       0 10316.7    0.06       0
#XS Ineff= 2 , 0
       0                               0
Bank Sta=9573.095,10316.7
Exp/Cntr=0.3,0.1

Type RM Length L Ch R = 1 ,10275.25,206.849100,206.849100,206.849100
XS GIS Cut Line= 6
825290.242853026 782433.01141225825276.537683821782607.632136407
825257.545702474782785.360913302825252.831959597782851.009603197
825253.367316381782948.332920794825266.893611954783109.625810876
#Sta/Elev= 30
9683.931333.49739706.039332.71239726.095331.16559766.207 329.1059836.404326.4211
 9886.63 323.6459916.807 322.7619926.867321.78179936.926319.03129957.045306.0445
9977.163297.86959987.222293.89469997.282293.605510007.33296.201510017.38301.5037
10047.51312.488510057.53314.896210077.58317.492610087.61 317.85610097.63319.1421
10137.66326.126210177.67329.405510217.72330.956210227.75330.538310237.78327.3294
10247.81321.621610257.84319.970310307.98331.153710348.16344.371510362.89346.9349
#Mann= 3 , 0 , 0
9683.931  0.0434       09683.931  0.0434       010362.89  0.0434       0
#XS Ineff= 2 , 0
       0                               0
Bank Sta=9683.931,10362.89
Exp/Cntr=0.3,0.1

Type RM Length L Ch R = 1 , 10068.4,285.650100,285.650100,285.650100
XS GIS Cut Line= 6
825180.333718152782369.816998715825043.486834383 782556.72244354
 825014.03985078782649.106559752 825023.93487397782696.003006388
825127.229185292782874.813801944825168.146795672783109.625810876
#Sta/Elev= 30
9553.829333.65669584.631332.41539663.178324.94139710.346 321.7039771.537315.6455
9804.543310.85899828.179309.22339909.832306.0092 9920.29305.99069955.422308.0127
9964.615305.9577 9976.76295.92339989.035292.26119991.973292.171610001.31292.9225
10025.92301.883210038.23 303.62110073.42305.507110128.52310.888910160.09309.3511
10180.86309.817110191.24311.367110211.73316.740110242.25323.272810272.68329.5011
10282.77330.876110302.95336.527710333.16343.122610343.21346.3088   10378352.7761
#Mann= 3 , 0 , 0
9553.829    0.04       09553.829    0.04       0   10378    0.04       0
#XS Ineff= 2 , 0
       0                               0
Bank Sta=9553.829,10378
Exp/Cntr=0.3,0.1

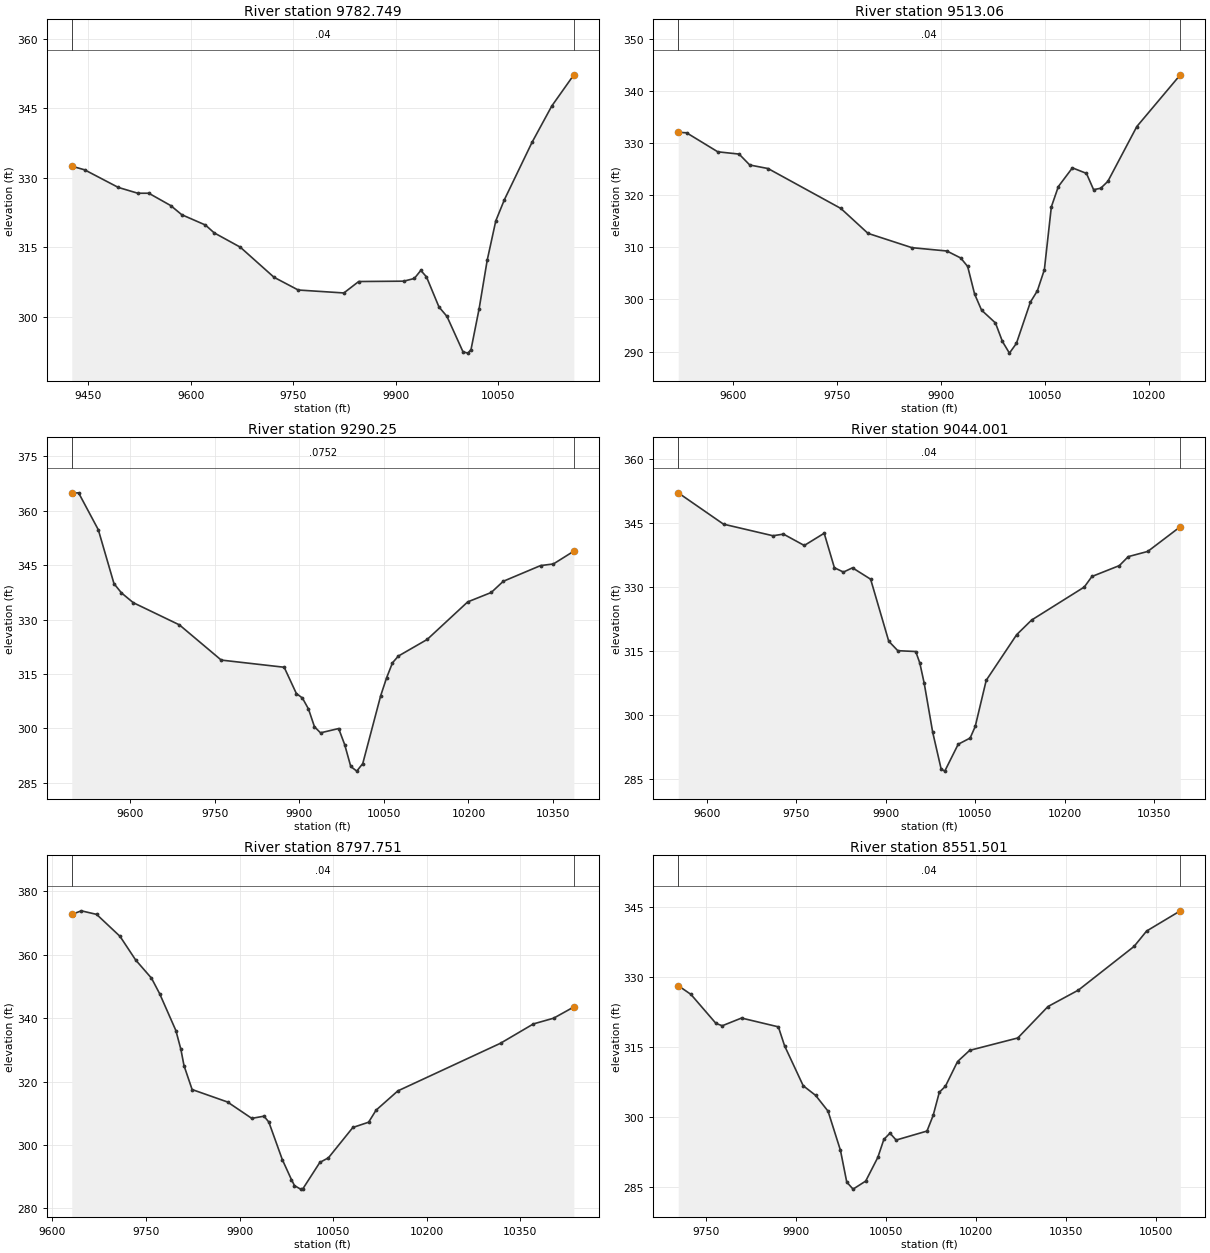
Type RM Length L Ch R = 1 ,9782.749,269.689100,269.689100,269.689100
XS GIS Cut Line= 6
825162.300580806782349.584698297824979.992886809782588.820473585
824891.344069375782768.470849475824869.140241163782790.329517447
824781.392244165782848.423557607824713.926035967782917.970614666
#Sta/Elev= 30
9425.635332.46969444.405331.68929493.701327.89079522.348326.63079538.429326.6324
9570.592323.96569586.673321.99999621.391319.7715 9634.16318.08379672.417314.9914
9721.807308.49619757.287305.74559824.126305.11219845.812307.57919911.829307.6571
9927.266308.2342 9936.78309.97519945.099308.58039963.364302.09329975.095300.0514
9998.557292.413510005.75292.126910010.32292.905310022.18301.705210034.03312.1892
 10046.6320.674710059.29325.273410099.67337.617910128.59345.4551 10160.9352.1839
#Mann= 3 , 0 , 0
9425.635    0.04       09425.635    0.04       0 10160.9    0.04       0
#XS Ineff= 2 , 0
       0                               0
Bank Sta=9425.635,10160.9
Exp/Cntr=0.3,0.1

Type RM Length L Ch R = 1 , 9513.06,222.810100,222.810100,222.810100
XS GIS Cut Line= 6
825149.658362499782335.400746063825035.409028659 782467.03614061
824942.125845324782530.916735305 824897.67169479782543.645689772
824646.153340346782571.498223135824517.018116319782614.694640288
#Sta/Elev= 30
9520.579332.09629532.546332.02319577.623328.36429608.375327.92769623.751325.8308
9650.147325.15039755.197317.48239794.306312.69779857.754309.94689908.058309.3097
9928.094307.96699938.112306.3391 9948.13301.03849958.148297.95119978.196295.4843
 9988.27291.9286 9998.35289.689510008.43291.559110028.59299.484610038.67301.6683
10048.75305.713510058.83317.786410068.95321.692110089.21325.283210109.49 324.217
10119.77321.089310130.06321.364310140.35322.687910182.15333.217710244.88343.1529
#Mann= 3 , 0 , 0
9520.579    0.04       09520.579    0.04       010244.88    0.04       0
#XS Ineff= 2 , 0
       0                               0
Bank Sta=9520.579,10244.88
Exp/Cntr=0.3,0.1

Type RM Length L Ch R = 1 , 9290.25,246.249600,246.249600,246.249600
XS GIS Cut Line= 6
 825192.59239868 782065.10823022825095.050998543782180.870350454
824970.783324205782269.075419077824739.755270577782361.865796103
824547.021052413782410.052949279824424.322118837782472.771618058
#Sta/Elev= 30
9496.416364.87369508.504364.95769543.473 354.7839571.312339.91049584.586337.3574
9605.482334.66299687.373 328.5379761.524318.83379873.184316.85459894.794309.6097
9905.513308.37279916.232305.36799926.951300.43339937.669298.76859969.826 299.954
9980.545295.49879991.263289.504510001.95288.207910012.58290.296410044.45309.0502
10054.94 313.97510065.26318.061410075.59319.926910126.87324.523710198.72334.8769
10240.48337.472810261.79340.557710327.95344.892910350.71345.3392   10387348.8725
#Mann= 3 , 0 , 0
9496.416  0.0752       09496.416  0.0752       0   10387  0.0752       0
#XS Ineff= 2 , 0
       0                               0
Bank Sta=9496.416,10387
Exp/Cntr=0.3,0.1

Type RM Length L Ch R = 1 ,9044.001,246.249600,246.249600,246.249600
XS GIS Cut Line= 6
824993.586782528781817.166838533824918.474005622781904.699206903
824850.072853856781971.748403549824635.423861484 782168.45147263
824463.088059951782303.009912202824377.404088736782386.843091018
#Sta/Elev= 30
9552.492352.09119628.323344.73949711.163342.01879728.754342.4034 9763.66339.7361
9797.002342.61059814.103 334.5079829.273333.49469844.443334.49519874.783331.8203
9905.124317.27519920.294315.04919950.348314.85229957.196312.14479964.552307.4018
9978.757295.91929992.961287.2556    9999286.786110021.46293.0911 10041.5 294.551
   10050297.260510068.44308.099810119.46  318.8110144.47322.237410232.68329.9814
10245.51332.458410291.47335.016210306.37337.118210339.06338.340810393.57344.1382
#Mann= 3 , 0 , 0
9552.492    0.04       09552.492    0.04       010393.57    0.04       0
#XS Ineff= 2 , 0
       0                               0
Bank Sta=9552.492,10393.57
Exp/Cntr=0.3,0.1

Type RM Length L Ch R = 1 ,8797.751,246.249600,246.249600,246.249600
XS GIS Cut Line= 6
824741.102385003781672.298083991824619.553810849781829.743339795
824458.973152914782002.873503058824434.628098976782034.404776715
 824394.52329239782104.771998341824300.811769978782334.936554619
#Sta/Elev= 30
9631.086372.70769646.392373.8395 9670.93372.7158 9708.45365.77919733.464358.3363
9758.858352.59929771.874347.72429797.907336.09279805.985330.12769810.924325.0454
 9823.94317.48069880.664313.55359919.519308.39079939.182309.0756 9946.92307.2121
9968.441295.4101 9983.07289.10049988.022287.1848  9997.7286.071610001.72 286.269
10028.68294.502610042.36295.939910081.58305.5159 10106.8307.174810118.69310.9613
10153.64317.051710318.29332.088510370.87338.170710403.32339.9819 10435.7343.5219
#Mann= 3 , 0 , 0
9631.086    0.04       09631.086    0.04       0 10435.7    0.04       0
#XS Ineff= 2 , 0
       0                               0
Bank Sta=9631.086,10435.7
Exp/Cntr=0.3,0.1

Type RM Length L Ch R = 1 ,8551.501,246.249600,246.249600,246.249600
XS GIS Cut Line= 6
824393.021038285781514.781249077824307.640374587781816.819961498
 824336.28279557781996.490878009824337.499456691782051.983924513
824321.912457791782176.917158539824279.757114388782328.620157941
#Sta/Elev= 30
9704.212328.21149725.327326.34069767.101320.10359777.544319.61589809.561321.2665
9870.895319.3784 9881.23315.31659912.237306.74959932.908304.68069953.579301.2984
 9974.26292.88949984.762 286.0739995.263284.575610016.26286.298610036.43291.3737
10046.47 295.22910056.66296.582110066.93295.099710118.29297.029110128.56300.3844
10138.84305.355110148.96306.638610169.15311.935410189.34314.3339 10269.5316.9962
10319.68323.733510370.37327.261610462.99336.6262 10483.9339.931610539.98344.2614
#Mann= 3 , 0 , 0
9704.212    0.04       09704.212    0.04       010539.98    0.04       0
#XS Ineff= 2 , 0
       0                               0
Bank Sta=9704.212,10539.98
Exp/Cntr=0.3,0.1

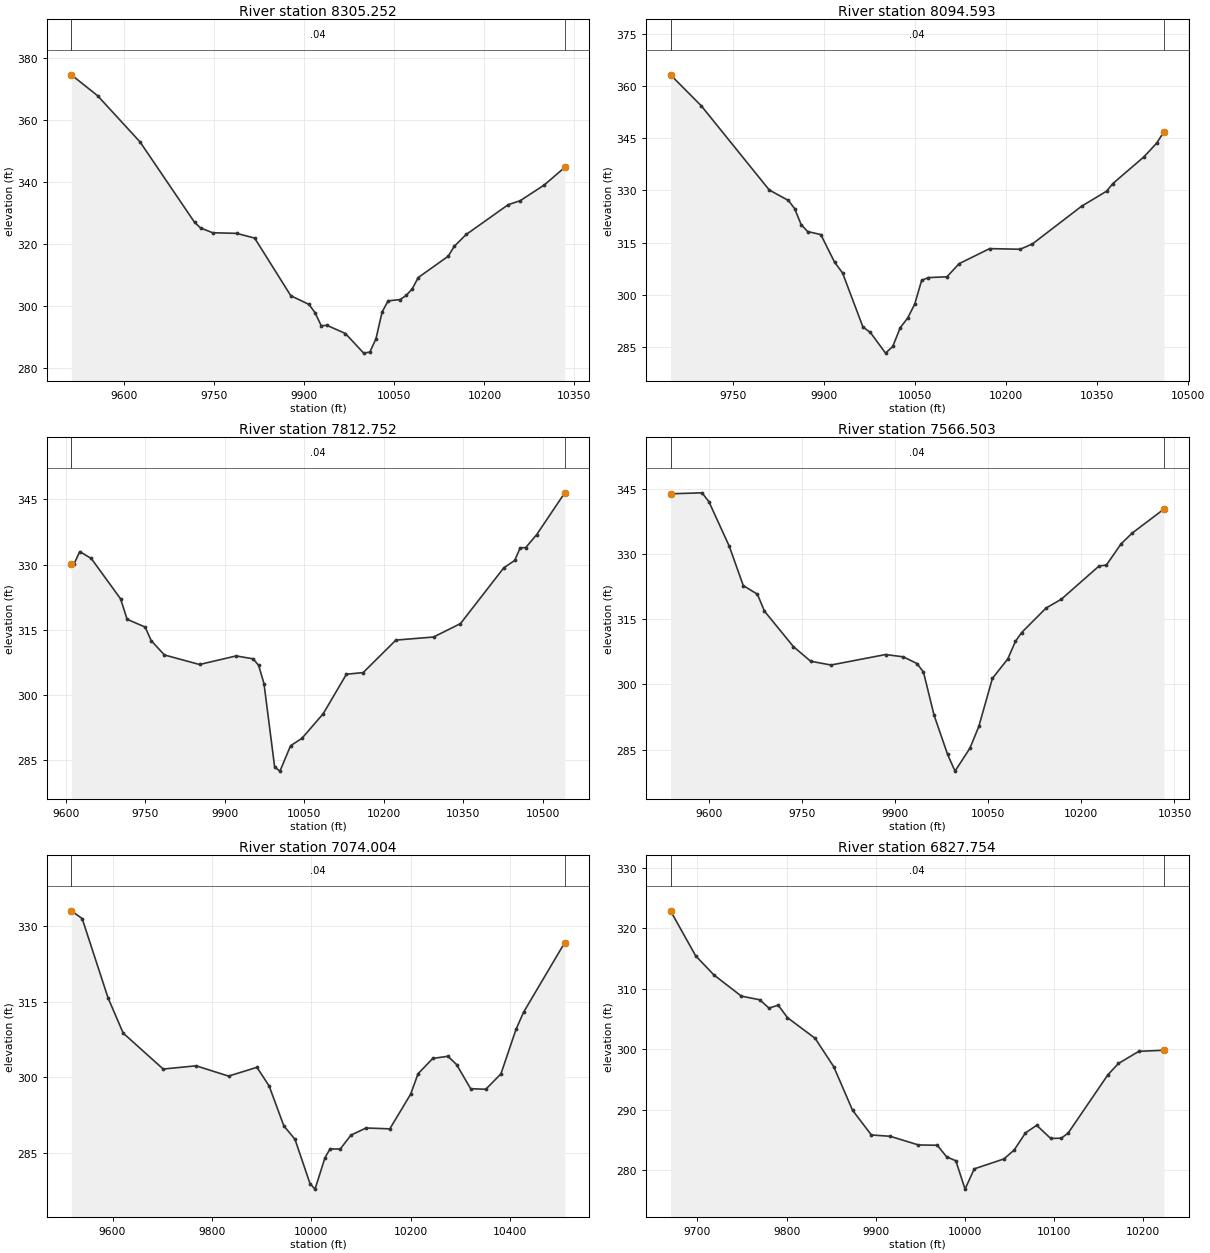
Type RM Length L Ch R = 1 ,8305.252,210.658600,210.658600,210.658600
XS GIS Cut Line= 6
 824180.59605539781471.883300623824146.380574764781722.357777402
824146.937611233781806.848806939824163.973851028781930.534978615
824148.295314091782044.357120069  824148.4395722782289.224895279
#Sta/Elev= 30
9511.462374.60529555.138 367.8789626.046352.9022 9716.85326.93699726.885325.1012
9746.954323.56889787.021323.36259817.036321.84019877.255303.20589907.564300.4001
9917.718297.71659927.871293.55249938.024293.59829968.308290.9916 9998.75284.6545
   10009285.0062 10019.2289.273410029.39297.915510039.47301.556310059.54301.9691
10069.57303.310410079.61305.397710089.64309.080810139.65315.983110149.65319.1764
10169.66323.008610239.66332.638810259.66333.921110299.66 338.99610333.89344.6925
#Mann= 3 , 0 , 0
9511.462    0.04       09511.462    0.04       010333.89    0.04       0
#XS Ineff= 2 , 0
       0                               0
Bank Sta=9511.462,10333.89
Exp/Cntr=0.3,0.1

Type RM Length L Ch R = 1 ,8094.593,281.840600,281.840600,281.840600
XS GIS Cut Line= 6
824108.582686328781494.880704701824067.032327622781698.811685403
823965.465643302781869.947236679 823952.03939256781918.822546843
823969.712327263782077.026055093824011.620490928782266.673141735
#Sta/Elev= 30
9647.085363.3328 9697.74354.40759809.796 330.1339841.111327.14239851.549324.7836
9862.227320.17879873.053318.15719894.706317.29139917.317309.34019930.525306.2234
9964.058 290.6619976.305289.085510001.37283.118110013.19285.032610025.55290.4506
10037.64293.186610049.46297.265110060.77304.0808 10071.6304.884510102.51305.1273
10122.56308.9043 10172.8313.238710223.21313.062410243.42314.604510324.61325.5023
10365.56329.797510375.83332.001510427.18339.7182 10447.9343.6336   10460346.8943
#Mann= 3 , 0 , 0
9647.085    0.04       09647.085    0.04       0   10460    0.04       0
#XS Ineff= 2 , 0
       0                               0
Bank Sta=9647.085,10460
Exp/Cntr=0.3,0.1

Type RM Length L Ch R = 1 ,7812.752,246.249600,246.249600,246.249600
XS GIS Cut Line= 6
823554.356864788781530.161658016823626.256235322781673.693462397
823696.195094527781750.489964411 823871.91047548781807.848752004
823915.107262836781918.194262764823988.117123799782266.332513226
#Sta/Elev= 30
9610.788330.16059615.934330.16199626.644333.00049648.384331.39969703.594322.1118
9715.928317.40449749.814315.61729761.513312.44959786.399 309.1799852.491306.9885
9921.511308.96059953.515308.29479963.882306.78749973.975302.59859994.094283.3793
 10004.1282.4323 10024.1288.284310045.57289.988110085.72295.669410129.39304.7427
10160.97305.130610222.66  312.6110293.73313.317110344.44  316.41 10426.1329.2559
10446.66330.949610456.97333.861110467.27333.889810487.88336.862810541.03346.5213
#Mann= 3 , 0 , 0
9610.788    0.04       09610.788    0.04       010541.03    0.04       0
#XS Ineff= 2 , 0
       0                               0
Bank Sta=9610.788,10541.03
Exp/Cntr=0.3,0.1

Type RM Length L Ch R = 1 ,7566.503,492.499200,492.499200,492.499200
XS GIS Cut Line= 6
823451.911930886781598.109828459823492.923299428781692.334242742
823554.590317205781797.886175946 823670.41615667 781950.11140238
823815.021024277782155.697891392823880.435274532782264.771906716
#Sta/Elev= 30
9537.999343.78859588.772344.01389599.765341.99949632.745331.71079655.225322.6889
 9677.99320.71449689.373316.81429736.034308.66099763.818305.30119796.604304.4321
9884.565306.84259913.069306.3111 9935.27304.76519945.613302.78929962.664292.9013
 9984.38283.91049996.415280.040410020.42285.305310034.75290.309110056.64301.3506
10081.36305.820410093.72309.844310103.69311.885810143.16 317.53410167.88319.5772
10228.56327.197610240.35327.411910263.91332.264610281.43334.706410333.06340.2758
#Mann= 3 , 0 , 0
9537.999    0.04       09537.999    0.04       010333.06    0.04       0
#XS Ineff= 2 , 0
       0                               0
Bank Sta=9537.999,10333.06
Exp/Cntr=0.3,0.1

Type RM Length L Ch R = 1 ,7074.004,246.249600,246.249600,246.249600
XS GIS Cut Line= 6
 823117.76087153781823.779327944823179.893339813782048.077554837
823261.523851007782204.348868936823290.279294997782223.723049492
823404.766969293782237.402532145823729.174105704  782519.3480331
#Sta/Elev= 30
9517.188332.99249538.967331.45929591.042315.74369621.472308.76569701.979301.6398
 9768.25302.28089833.407300.24219890.565301.98199915.117298.28529944.609290.3953
9967.064287.71919997.347278.937710007.41277.844910027.52284.100210037.58285.8016
10058.11285.797310079.81288.555410110.17289.958710157.84289.790110199.75296.6539
 10214.6300.700410244.32 303.74910274.77304.168610292.12302.535710320.46297.7449
10350.91297.633810381.37300.682110411.82309.531410427.05312.918110509.81326.7075
#Mann= 3 , 0 , 0
9517.188    0.04       09517.188    0.04       010509.81    0.04       0
#XS Ineff= 2 , 0
       0                10086.43       0
Bank Sta=9517.188,10509.81
Exp/Cntr=0.3,0.1

Type RM Length L Ch R = 1 ,6827.754,263.640600,263.640600,263.640600
XS GIS Cut Line= 6
 823046.42574397781957.342970961823089.276448621 782130.94112058
 823147.08520735782304.200959393823178.871329925782350.612898857
823198.953942172782370.350912435823290.108466309782426.836740268
#Sta/Elev= 30
9669.744322.8954 9698.03315.44379718.516312.28819749.244308.79529769.883308.1912
9780.251306.81269790.618307.29989800.985 305.2389832.087301.81469852.902297.1318
9874.034289.93449895.165 285.8419916.297 285.6249947.994 284.1919969.126284.1418
9979.588282.23489989.967281.571210000.31276.888210010.62280.240210043.87281.8756
10055.45283.357610068.08286.179710080.71287.444210096.39285.268610108.32285.3111
10115.96286.147310160.67295.803210172.48297.665610195.33299.663510223.52 299.853
#Mann= 3 , 0 , 0
9669.744    0.04       09669.744    0.04       010223.52    0.04       0
#XS Ineff= 2 , 0
       09938.589                       0
Bank Sta=9669.744,10223.52
Exp/Cntr=0.3,0.1

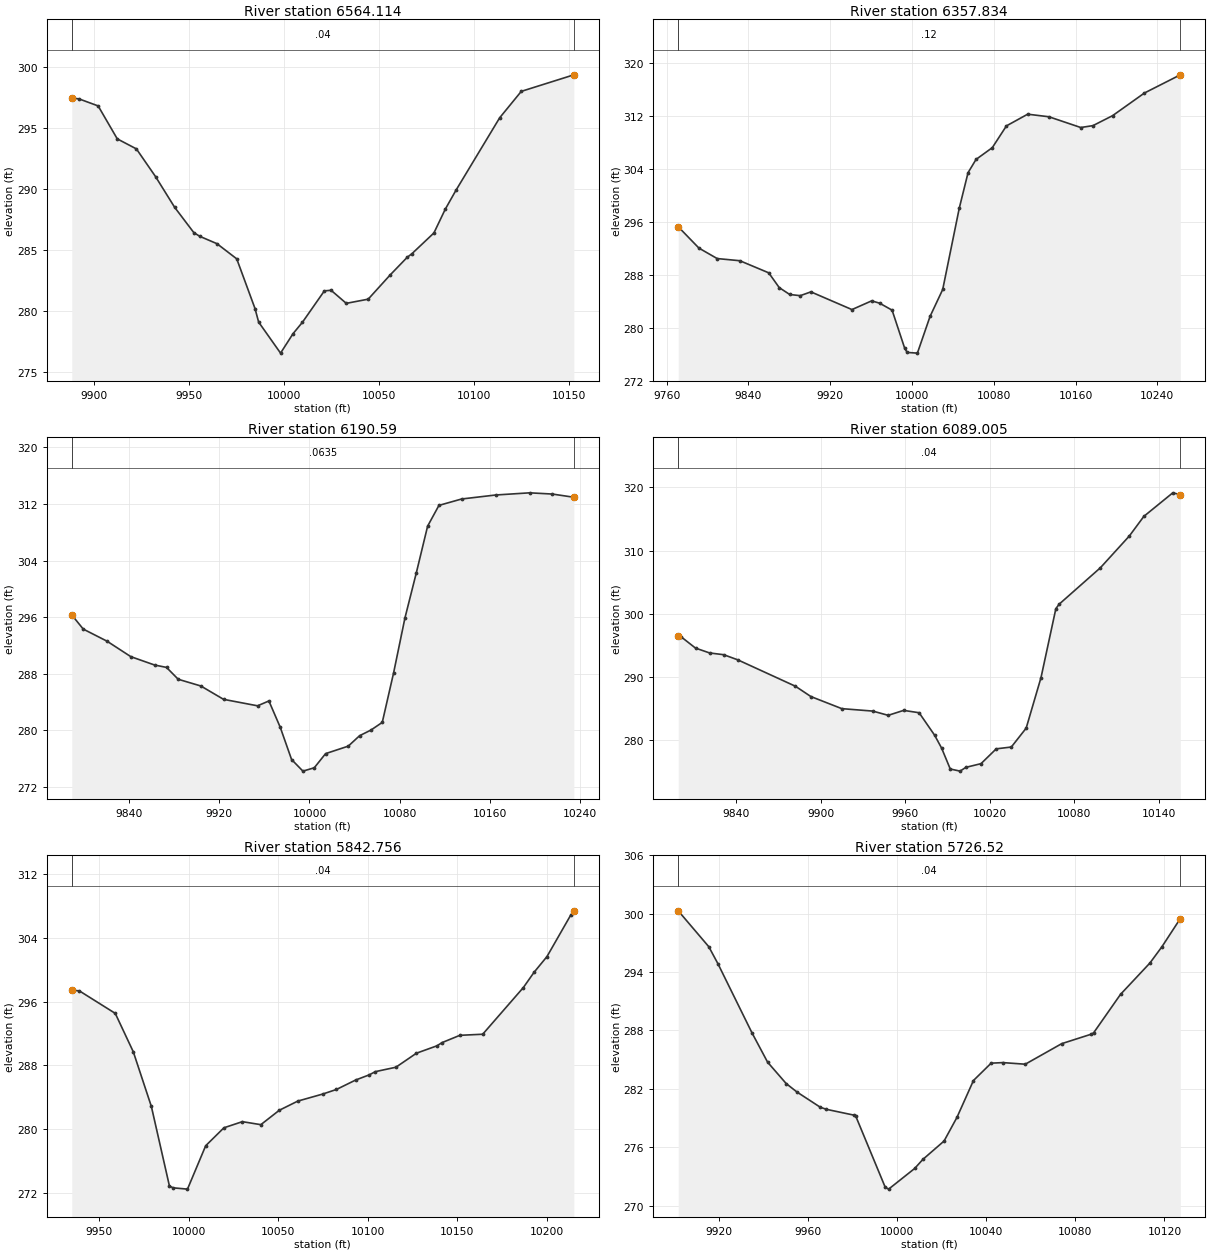
Type RM Length L Ch R = 1 ,6564.114,206.279800,206.279800,206.279800
XS GIS Cut Line= 3
823041.209726334782547.711596623823108.134988576782539.516666546
823278.862698346782441.177505717
#Sta/Elev= 29
9888.135297.48179891.953297.41399902.028296.83659912.103294.13249922.177293.3114
9932.252291.03929942.327288.51729952.401286.4453 9955.56286.13769964.609285.5342
9975.022284.29049984.644280.21469986.563 279.1029998.103276.555610004.68278.1524
10009.64  279.0910021.18281.662810024.71281.712410032.72280.639610044.26280.9823
 10055.8282.963710064.78284.411410067.34284.719110078.88286.414510084.82 288.352
10090.43289.900310113.51295.862110124.89298.030410152.58299.3876
#Mann= 3 , 0 , 0
9888.135    0.04       09888.135    0.04       010152.58    0.04       0
#XS Ineff= 2 , 0
       0                               0
Bank Sta=9888.135,10152.58
Exp/Cntr=0.3,0.1

Type RM Length L Ch R = 1 ,6357.834,167.243700,167.243700,167.243700
XS GIS Cut Line= 6
823056.264116347782560.633787289823093.941572219782639.514585271
823129.627326369782647.838175997 823179.04623571782668.712172985
823290.868168116782750.998962715823458.756589174782798.059122354
#Sta/Elev= 30
9771.357 295.2469791.625292.01919809.442290.44189831.606290.11449859.861288.2861
9870.129286.05539880.398285.01229890.666284.83519901.136285.40759941.275282.7319
9960.546284.05019968.338 283.697 9980.53282.64469992.907276.86379995.323276.2541
10005.28276.151410017.66281.698710030.04 285.76810046.23298.047610054.82303.4166
10062.63305.420210078.54307.198610092.37310.490810113.15312.257210133.92311.8682
10165.07310.243910177.01 310.52910196.23 312.03810227.38315.460310262.44318.2054
#Mann= 3 , 0 , 0
9771.357    0.12       09771.357    0.12       010262.44    0.12       0
#XS Ineff= 2 , 0
       0                               0
Bank Sta=9771.357,10262.44
Exp/Cntr=0.3,0.1

Type RM Length L Ch R = 1 , 6190.59,101.584700,101.584700,101.584700
XS GIS Cut Line= 3
 823046.08874484782575.331546116 823075.00000003782661.568618119
823111.663361192783014.003117606
#Sta/Elev= 30
9789.183296.31019799.381294.30549820.475292.59439841.569290.40589862.663289.2225
 9873.21288.88589883.588287.20829903.696286.25459923.804284.36789953.965283.4518
9964.019 284.1399974.073280.41599984.127275.85389994.181274.210910004.24274.6834
10014.29276.6863 10034.4277.745310044.45279.221910054.51280.020110064.56 281.106
10074.61288.109810084.67295.878910094.72302.236610104.77 308.86810114.83311.8097
10134.94312.7138 10165.1313.278810195.26313.586510215.37313.414210234.47312.9594
#Mann= 3 , 0 , 0
9789.183  0.0635       09789.183  0.0635       010234.47  0.0635       0
#XS Ineff= 2 , 0
       0                               0
Bank Sta=9789.183,10234.47
Exp/Cntr=0.3,0.1

Type RM Length L Ch R = 1 ,6089.005,246.249600,246.249600,246.249600
XS GIS Cut Line= 6
823042.108133435782572.733449757823042.108133435782645.650116444
822988.449223689782763.117124105822976.868360184782791.526688707
822955.258543862782856.527528501822942.774540185782910.198945991
#Sta/Elev= 30
9798.934 296.4399801.201296.33099811.201294.58729821.201293.81949831.201293.5401
9841.201292.7289 9882.11288.55429893.082286.92499915.026285.0115 9936.97284.6276
9947.942 283.9569958.914284.73719969.886284.36619980.891280.81589985.875278.7657
9992.003 275.467    9999275.132310003.03275.725810013.83276.314110024.63278.6556
10035.34278.943510045.88281.929410056.42289.931610066.95300.8213 10069.3301.5315
10098.57307.291610119.14 312.32410129.41315.416510149.94 319.13810155.28318.8507
#Mann= 3 , 0 , 0
9798.934    0.04       09798.934    0.04       010155.28    0.04       0
#XS Ineff= 2 , 0
       0                               0
Bank Sta=9798.934,10155.28
Exp/Cntr=0.3,0.1

Type RM Length L Ch R = 1 ,5842.756,116.235600,116.235600,116.235600
XS GIS Cut Line= 6
823029.246601608782549.905879694822946.486650221782559.373289094
822905.669104383782569.582518567822867.863736086 782584.71519764
822807.587190281782624.957469564822780.524907609782656.359787183
#Sta/Elev= 30
9934.756297.43169939.003297.3461 9959.04294.52789969.123 289.7079979.207282.8606
9989.291272.89729991.359272.66529999.378272.503110009.54277.939810019.72280.1894
10030.03280.957610040.34280.580610050.64282.384810060.98283.536210074.84284.4135
10082.53284.9902 10093.3286.176610100.98 286.83310104.27287.225510115.75 287.778
10127.24289.537810138.75290.467310141.46 290.85810151.49291.778210164.23291.9134
10186.93297.764310192.96299.690410200.13301.647810213.33306.821910215.13307.3784
#Mann= 3 , 0 , 0
9934.756    0.04       09934.756    0.04       010215.13    0.04       0
#XS Ineff= 2 , 0
       0                               0
Bank Sta=9934.756,10215.13
Exp/Cntr=0.3,0.1

Type RM Length L Ch R = 1 , 5726.52,134.807800,134.807800,134.807800
XS GIS Cut Line= 2
822946.596223474782404.611424223822799.618635088782575.331546128
#Sta/Elev= 28
9901.845300.28349915.554296.59639919.619294.86439934.946287.73919941.945284.7304
9950.273282.5347 9955.14281.6602  9965.6280.09679968.335279.88499980.927279.2757
9981.531 279.1649994.726271.87259996.254271.684110007.92273.804610011.58 274.732
10021.12276.627210026.91279.058710034.31 282.84710042.24284.628510047.51284.6863
10057.56284.5217 10073.9286.632610087.09287.600710088.22287.745110100.29 291.698
10113.49294.921810118.87296.591410127.12299.4879
#Mann= 3 , 0 , 0
9901.845    0.04       09901.845    0.04       010127.12    0.04       0
#XS Ineff= 2 , 0
       0                               0
Bank Sta=9901.845,10127.12
Exp/Cntr=0.3,0.1

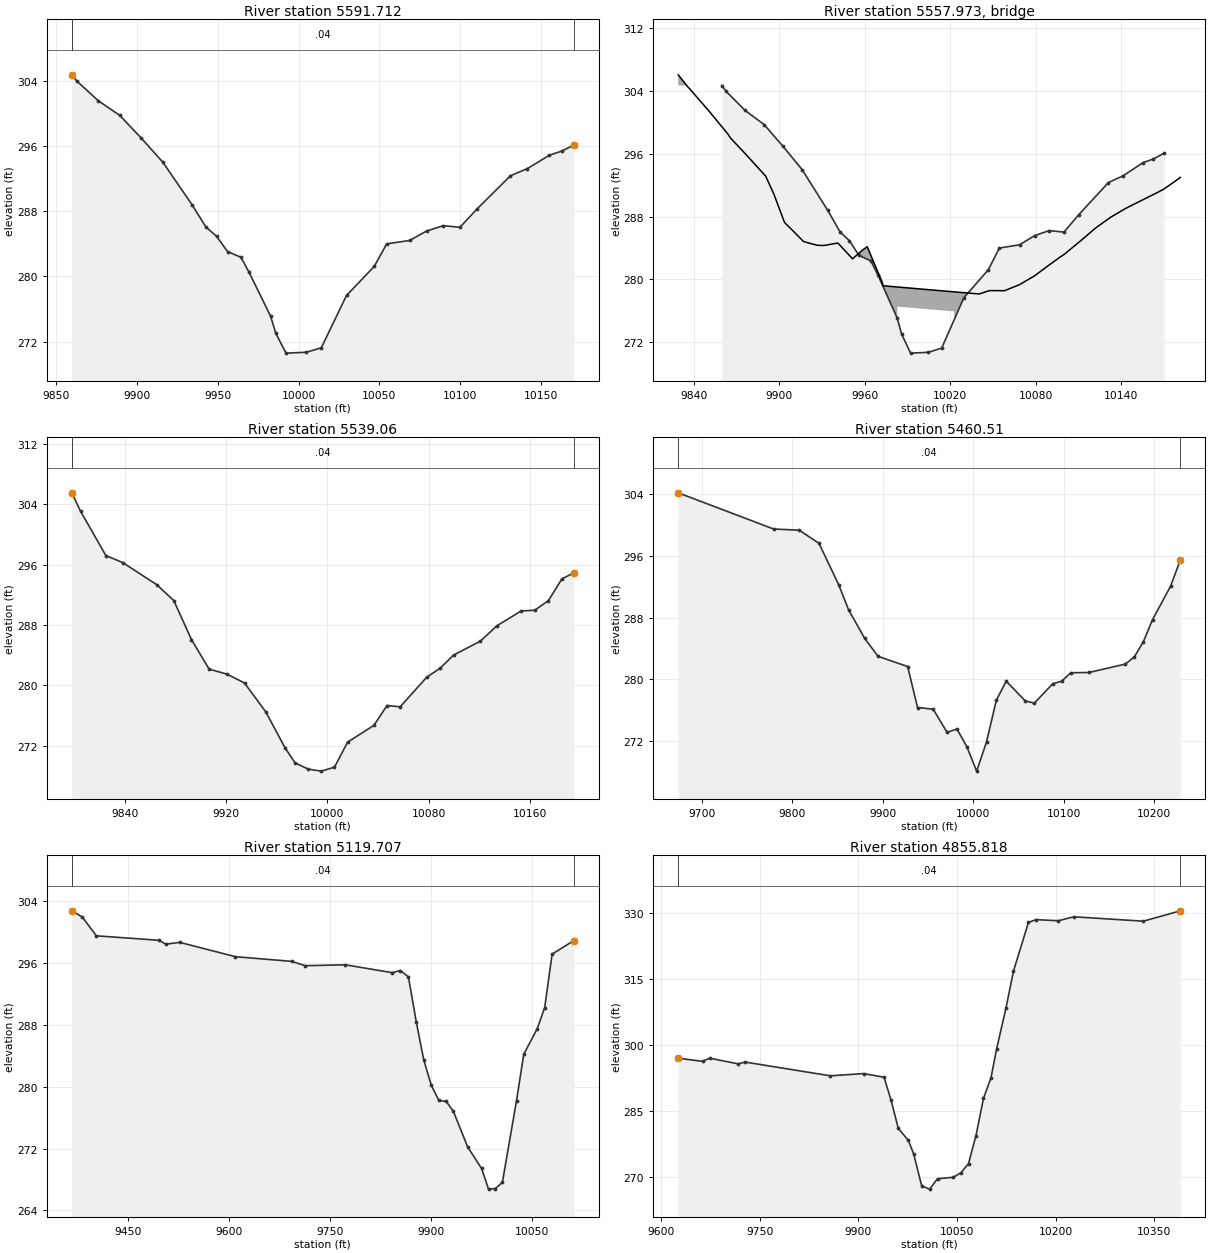
Type RM Length L Ch R = 1 ,5591.712,52.652500,52.652500,52.652500
XS GIS Cut Line= 5
822927.310337543782275.840506524822832.577963084782359.239866897
822797.461823672782439.214250535822786.553960145782483.205481052
822770.227392226782532.232650205
#Sta/Elev= 30
9859.743304.71529862.821303.96239876.144301.53659889.468299.73369902.791296.9404
9916.114293.99059934.139288.7783 9942.76286.04019949.273284.92749956.083283.0421
9964.406 282.3419969.406280.50569982.729275.10859985.956 273.0169992.247270.5864
 10004.8270.690510014.09 271.23910029.68277.655810046.85281.226510054.55283.9908
 10068.7284.398910079.26 285.56510089.56286.214910099.87286.018510110.17288.2174
10131.06292.3336 10141.6293.222510155.19294.860510162.67295.3509 10170.3296.1015
#Mann= 3 , 0 , 0
9859.743    0.04       09859.743    0.04       0 10170.3    0.04       0
#XS Ineff= 2 , 0
       0                               0
Bank Sta=9859.743,10170.3
Exp/Cntr=0.3,0.1

Type RM Length L Ch R = 3 ,5557.973,,,
BEGIN DESCRIPTION:
END DESCRIPTION:
Bridge Culvert--1,0,-1,-1, 0
Deck Dist Width WeirC Skew NumUp NumDn MinLoCord MaxHiCord MaxSubmerge Is_Ogee
16.326250,20.000000,2.6,0, 48, 48, , , 0.95, 0, 0,0,,
 9829.17 9835.71 9837.14 9850.46 9850.84 9863.79 9865.97 9877.11 9881.10 9890.44
 9896.23 9903.76 9911.36 9917.09 9926.49 9930.41 9932.69 9941.21 9951.50 9958.05
 9961.78 9972.06 9973.00 9982.92 9982.9210022.9210022.9210040.4210047.5310053.13
10058.0610068.6010079.1310084.9210089.6710096.9110100.2610110.9810114.1810121.70
10132.4310141.9110143.1510153.8710164.5910169.6410175.3110181.55
  306.08  304.58  304.31  301.52  301.44  298.58  298.00  295.84  295.04  293.19
  290.90  287.25  285.88  284.82  284.35  284.31  284.35  284.63  282.61  283.66
  284.17  279.74  279.18  279.02  279.02  278.40  278.40  278.13  278.56  278.56
  278.54  279.31  280.43  281.21  281.85  282.80  283.21  284.82  285.31  286.49
  287.89  288.91  289.04  290.02  290.99  291.47  292.18  292.99
 -693.92 -695.42 -695.69 -698.48 -698.56 -701.42 -702.00 -704.16 -704.96 -706.81
 -709.10 -712.75 -714.12 -715.18 -715.65 -715.69 -715.65 -715.37 -717.39 -716.34
 -715.83 -720.26 -720.82 -720.98  276.52  275.90 -721.60 -721.87 -721.44 -721.44
 -721.46 -720.69 -719.57 -718.79 -718.15 -717.20 -716.79 -715.18 -714.69 -713.51
 -712.11 -711.09 -710.96 -709.98 -709.01 -708.53 -707.82 -707.01
 9829.17 9835.71 9837.14 9850.46 9850.84 9863.79 9865.97 9877.11 9881.10 9890.44
 9896.23 9903.76 9911.36 9917.09 9926.49 9930.41 9932.69 9941.21 9951.50 9958.05
 9961.78 9972.06 9973.00 9975.58 9975.5810015.5810015.5810040.4210047.5310053.13
10058.0610068.6010079.1310084.9210089.6710096.9110100.2610110.9810114.1810121.70
10132.4310141.9110143.1510153.8710164.5910169.6410175.3110181.55
  306.08  304.58  304.31  301.52  301.44  298.58  298.00  295.84  295.04  293.19
  290.90  287.25  285.88  284.82  284.35  284.31  284.35  284.63  282.61  283.66
  284.17  279.74  279.18  279.14  279.14  278.52  278.52  278.13  278.56  278.56
  278.54  279.31  280.43  281.21  281.85  282.80  283.21  284.82  285.31  286.49
  287.89  288.91  289.04  290.02  290.99  291.47  292.18  292.99
 -693.92 -695.42 -695.69 -698.48 -698.56 -701.42 -702.00 -704.16 -704.96 -706.81
 -709.10 -712.75 -714.12 -715.18 -715.65 -715.69 -715.65 -715.37 -717.39 -716.34
 -715.83 -720.26 -720.82 -720.86  276.64  276.02 -721.48 -721.87 -721.44 -721.44
 -721.46 -720.69 -719.57 -718.79 -718.15 -717.20 -716.79 -715.18 -714.69 -713.51
 -712.11 -711.09 -710.96 -709.98 -709.01 -708.53 -707.82 -707.01
BR Coef=-1 , 0 , 0 ,, 0 ,,,0.8,0,1,0,
WSPro=,,,, 1 ,,,, 0 ,,,, 0 ,,,,-1 ,-1 ,-1 , 0 , 0 , 0 , 0 , 0
BC Design=,, 0 ,, 0 ,,,,,,

Type RM Length L Ch R = 1 , 5539.06,78.550100,78.550100,78.550100
XS GIS Cut Line= 6
822915.172852993782190.396335781822858.622261375782240.634292424
822796.800704032 782301.01254487822765.998152792782409.693244457
822747.871127635 782459.89116028 822722.46451965782523.729669094
#Sta/Elev= 30
9797.783305.49769804.715 303.0729824.766297.19369838.143296.25899864.895  293.35
9878.489291.23839892.467286.06339906.445282.15939920.423281.50299934.401280.3265
9951.235276.49599966.444 271.7469974.379269.75599984.772268.92019995.166268.6571
10005.56269.181610015.95272.494810036.74274.712710047.14277.342210057.53277.1703
10078.44281.076110089.08 282.27410099.71284.013310120.97285.863910133.94287.8862
 10153.2289.860310163.96289.956410174.72291.221210185.48  294.1110194.88294.9055
#Mann= 3 , 0 , 0
9797.783    0.04       09797.783    0.04       010194.88    0.04       0
#XS Ineff= 2 , 0
       0                10068.62       0
Bank Sta=9797.783,10194.88
Exp/Cntr=0.3,0.1

Type RM Length L Ch R = 1 , 5460.51,340.803200,340.803200,340.803200
XS GIS Cut Line= 4
822847.111301482782002.440300137822787.381027341782139.484242991
 822697.86492008782346.950985715 822713.69327575 782525.58528544
#Sta/Elev= 30
9673.863304.1903 9779.26299.49699807.557 299.3429829.368 297.6469851.147292.2737
9862.038289.03469879.851285.31219894.712282.97689927.385281.65459938.276276.3395
9955.577276.1226 9970.95273.11559981.841273.55189992.732271.256710003.62268.0861
10014.51271.871110025.41277.3038 10036.3279.753410057.39277.190310067.43276.9078
10087.51279.406810097.55279.758310107.59280.845910127.67280.881910167.82281.9689
10177.86282.9019 10187.9284.893610197.94287.739410218.02 292.10210228.65295.4902
#Mann= 3 , 0 , 0
9673.863    0.04       09673.863    0.04       010228.65    0.04       0
#XS Ineff= 2 , 0
       0                               0
Bank Sta=9673.863,10228.65
Exp/Cntr=0.3,0.1

Type RM Length L Ch R = 1 ,5119.707,263.888500,263.888500,263.888500
XS GIS Cut Line= 6
822322.237171352781989.765782773822409.475601643782322.730927065
822436.220454007782363.376749232822519.586068273782438.391795278
822690.029615045782502.295511872822714.603653818782554.150080234
#Sta/Elev= 30
 9366.29302.77949382.038301.96979402.713299.54449495.751 298.9659506.089298.4656
9526.764298.69429609.464296.83919692.835 296.237 9713.26295.67129772.872295.7919
9842.239294.7737 9854.37295.04469866.501294.23029878.132288.4142 9889.34283.4577
9900.547280.17149911.754278.22039922.799278.09529933.378276.80149954.536272.2056
9975.238269.41599985.536266.74349995.835 266.82210006.16267.633310027.15 278.215
10037.88284.206310057.91287.522410068.97290.245910080.04297.1702 10112.3298.9286
#Mann= 3 , 0 , 0
 9366.29    0.04       0 9366.29    0.04       0 10112.3    0.04       0
#XS Ineff= 2 , 0
       0                               0
Bank Sta=9366.29,10112.3
Exp/Cntr=0.3,0.1

Type RM Length L Ch R = 1 ,4855.818,167.265000,167.265000,167.265000
XS GIS Cut Line= 6
822306.900617003782260.654374212  822394.6193977782476.430127442
822391.492751628782529.088817209822405.980242461782572.882009745
822580.999175608782870.144447595822628.902383149782941.668683231
#Sta/Elev= 30
9626.314297.02849663.389296.29719674.184297.01829717.363295.73779728.158296.1408
9857.695293.02219908.106  293.539939.259 292.706 9950.01287.44469960.941281.0904
9976.298278.35099984.337275.28939996.517268.043510008.57267.318710020.56269.6791
10044.55270.004910056.29 271.04110067.69273.101410079.08  279.4810090.47 287.902
10101.87292.569310110.49299.180110124.65308.388410136.05316.771910158.84327.8203
10170.23328.451410204.45328.204910227.75329.102210333.57328.102310389.74330.4518
#Mann= 3 , 0 , 0
9626.314    0.04       09626.314    0.04       010389.74    0.04       0
#XS Ineff= 2 , 0
       0                               0
Bank Sta=9626.314,10389.74
Exp/Cntr=0.3,0.1

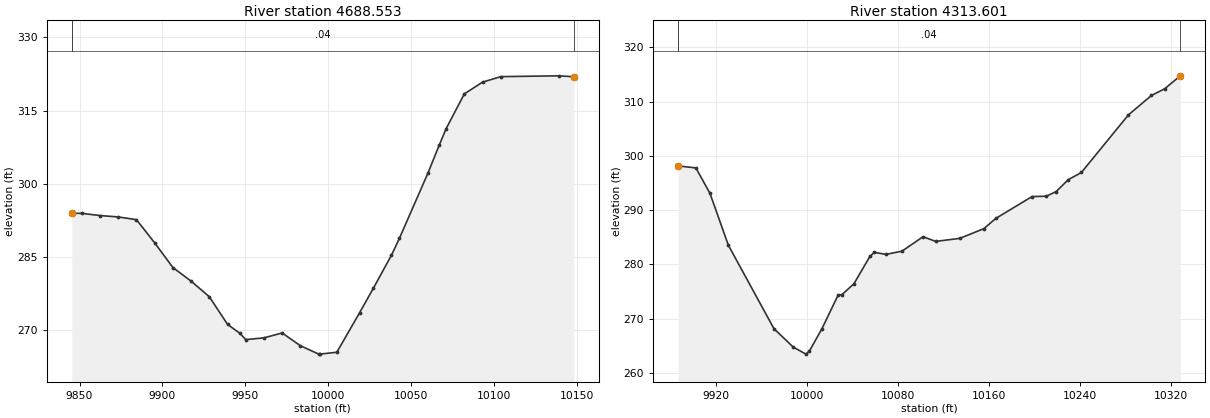
Type RM Length L Ch R = 1 ,4688.553,374.952100,374.952100,374.952100
XS GIS Cut Line= 2
822347.151538819782519.497467786822221.283483297782795.105106667
#Sta/Elev= 30
9845.302293.94469851.351293.91269862.345293.46729873.338293.17599884.332292.6199
9895.325287.87219906.319   282.89917.312280.00859928.306276.80869939.299271.1429
9946.769269.30159950.293268.00819961.286268.3694 9972.28269.37329983.273266.7523
9994.267265.04479994.913265.032110005.26265.417710018.98273.509610027.25278.5211
10038.24285.330810043.06288.821710060.23302.162510067.13307.979210071.22311.2951
10082.21318.430210093.21320.8367 10104.2321.966210139.34322.132110148.29 321.938
#Mann= 3 , 0 , 0
9845.302    0.04       09845.302    0.04       010148.29    0.04       0
#XS Ineff= 2 , 0
       0                               0
Bank Sta=9845.302,10148.29
Exp/Cntr=0.3,0.1

Type RM Length L Ch R = 1 ,4313.601,0.000000,0.000000,0.000000
XS GIS Cut Line= 3
822204.832919955782254.138550073822050.444484323782406.321436629
822123.227603972782618.054148361
#Sta/Elev= 30
9887.242298.14029902.714297.7831 9915.09293.09459931.204283.55059971.256268.1634
9988.184 264.7769999.339263.481110002.43264.072610013.38268.163910027.42274.2907
10030.92274.439710041.46 276.441 10055.5281.488510059.41 282.22410069.55 281.854
10083.59282.440410102.14285.1061 10113.2 284.24410134.35284.8014 10155.5286.5911
10166.07288.4905 10197.8292.503110210.32292.561810218.95293.423510229.52295.6021
10241.09296.935710282.39307.550910302.61311.127110314.12312.345510327.92314.7405
#Mann= 3 , 0 , 0
9887.242    0.04       09887.242    0.04       010327.92    0.04       0
#XS Ineff= 2 , 0
       0                               0
Bank Sta=9887.242,10327.92
Exp/Cntr=0.3,0.1